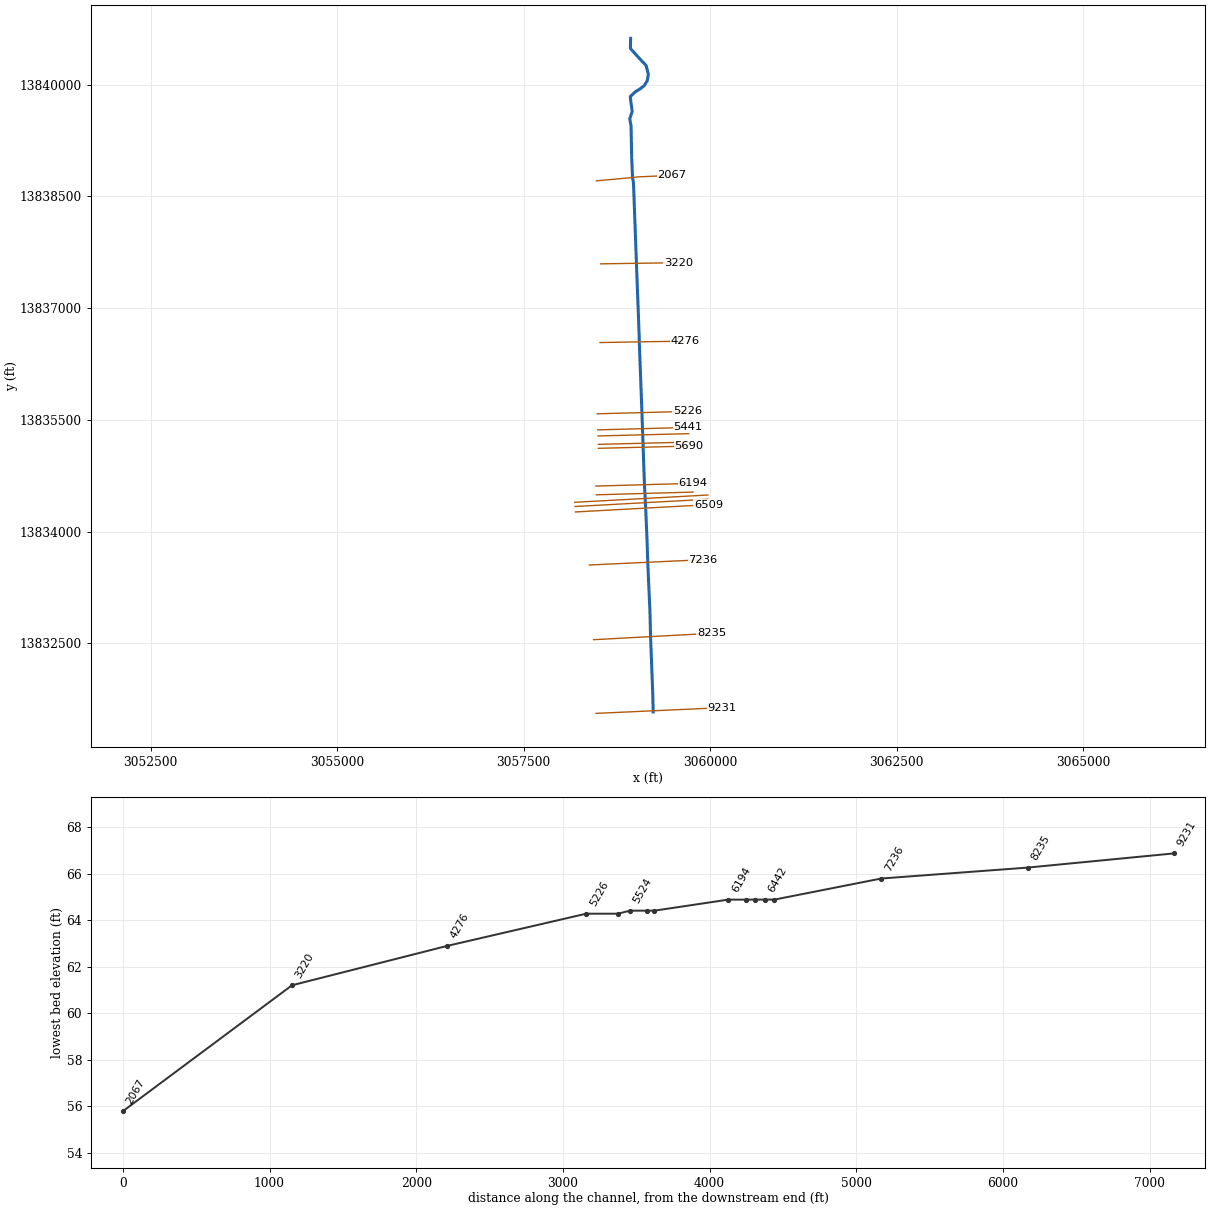
--- W157-00-00.prj (project) ---

Proj Title=W157-00-00
Current Plan=p02
Default Exp/Contr=.3,.1
English Units
Geom File=g01
Flow File=f01
Flow File=f02
Plan File=p01
Plan File=p02
Y Axis Title=Elevation
X Axis Title(PF)=Main Channel Distance
X Axis Title(XS)=Station
BEGIN DESCRIPTION:
Buffalo Bayou Watershed
Unnamed Tributary W157-00-00
HCFCD Unit W157-00-00
Flood Hazard Model
10%, 2%, 1%, and 0.2% Events
Filename: W157-00-00.prj
Prepared by: JAS DATE: 05/13/2003
Reviewed by: Alem Gebriel, Joe Barrow
STATUS:  Final RAS
END DESCRIPTION:
DSS Export Rating Curves= 0
DSS Export Rating Curve Sorted= 0
DSS Export Volume Flow Curves= 0
DXF OffsetX= 0
DXF OffsetY= 0
DXF ScaleX= 1
DXF ScaleY= 10

--- W157-00-00.p02 (plan) ---

Plan Title=Floodway Revised Sept 2009
Version=Version 3.0.1  Mar 2001
Short Identifier=FW-M3
Geom File=g01
Flow File=f02
Subcritical Flow
K Sum by GR= 0
Std Step Tol= 0.01
Critical Tol= 0.01
Num of Std Step Trials= 20
Max Error Tol= 0.3
Flow Tol Ratio= 0.001
Split Flow NTrial= 30
Split Flow Tol= 0.02
Split Flow Ratio= 0.02
Log Output Level= 0
Friction Slope Method= 1
Unsteady Friction Slope Method= 2
Parabolic Critical Depth
Global Vel Dist= 0 , 0 , 0
Global Log Level= 0
CheckData=True
Encroach Param=-1 ,0,0, 2
Encroach River=Buffalo Bayou
Encroach Reach=W157-00-00
Encroach Node=9231
       1  747.55  786.06
Encroach Node=8235
       1   741.4  784.34
Encroach Node=7236
       1  759.58  806.86
Encroach Node=6509
       1  923.53  965.39
Encroach Node=6442
       1  923.53  965.39
Encroach Node=6407.692
       4       1
Encroach Node=6379
       1  923.53  965.39
Encroach Node=6312
       1  631.66  675.84
Encroach Node=6194
       1  631.66  675.84
Encroach Node=5690
       1  572.02  623.62
Encroach Node=5637
       1  572.02  623.62
Encroach Node=5581.178
       4       1
Encroach Node=5524
       1  572.02  623.62
Encroach Node=5441
       1  574.27  622.12
Encroach Node=5226
       1  574.27  622.12
Encroach Node=4276
       1  495.87   542.9
Encroach Node=3220
       1  442.34  500.22
Encroach Node=2067
       1  449.61  514.63
Encroach Node=1804
       1  415.29  466.72
Encroach Node=1721
       1  415.29  466.72
Encroach Node=1699.700
       1  415.29  466.72
Encroach Node=1677
       1  415.29  466.72
Encroach Node=1543
       1  415.29  466.72
Encroach Node=1276
       1  451.73  504.32
Encroach Node=963
       1  456.57  480.17
Encroach Node=313
       1  479.93   506.1
Encroach Node=119
       1  468.45   520.6
BEGIN DESCRIPTION:
Revised M3 Floodway - Original M3 floodway model Steady Flow Change Locations did not match FH. (GA Sept 2009)
END DESCRIPTION:
Computation Interval=1HOUR
Output Interval=1HOUR
Run HTab= 0
Run UNet= 0
Run PostProcess= 0
UNET Theta= 1
UNET ZTol= 0.02
UNET ZSATol= 0.1
UNET MxIter= 20
UNET MaxInSteps= 20
UNET DtIC= 0
UNET DtMin= 0
UNET MaxCRTS= 20
UNET WFStab= 2
UNET SFStab= 1
UNET WFX= 1
UNET SFX= 1
UNET Convert EG Bridges=-1
UNET Use Existing IB Tables=-1
Instantaneous Interval=1HOUR
Write IC File= 0
IC Time=0
Write Velocity= 0
Write Detailed= 0

--- W157-00-00.p01 (plan) ---

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Plan Title=FEMA Effective June 2007
Short Identifier=FH-M3
Geom File=g01
Flow File=f01
Encroach Param=-1 ,0,0, 0

--- W157-00-00.f02 (steady flow) ---

Flow Title=W157-Floodway
Version=Version 3.0.1  Mar 2001
Number of Profiles= 2
Profile Names=1PCT_100yr,Floodway
River Rch & RM=W157-00-00,W157-00-00      ,9231
     102     102
River Rch & RM=W157-00-00,W157-00-00      ,6442
     111     111
River Rch & RM=W157-00-00,W157-00-00      ,5637
     146     146
River Rch & RM=W157-00-00,W157-00-00      ,3220
     219     219
River Rch & RM=W157-00-00,W157-00-00      ,1721
     264     264
River Rch & RM=W157-00-00,W157-00-00      ,119
     347     347
Boundary for River Rch & Prof#=W157-00-00,W157-00-00      , 1
Up Type= 0
Dn Type= 3
Dn Slope=.004
Boundary for River Rch & Prof#=W157-00-00,W157-00-00      , 2
Up Type= 0
Dn Type= 3
Dn Slope=.004
DSS Import GetInterval= 0
DSS Import GetPeak= 0
DSS Import FillOption= 0

--- W157-00-00.f01 (steady flow) ---

Flow Title=FEMA Effective June 2007
Version=Version 3.0.1  Mar 2001
Number of Profiles= 4
Profile Names=10PCT_10yr,2PCT_50yr,1PCT_100yr,0.2PCT_500yr
River Rch & RM=Buffalo Bayou,W157-00-00      ,9231
      55      85     102     153
River Rch & RM=Buffalo Bayou,W157-00-00      ,6442
      60      93     111     166
River Rch & RM=Buffalo Bayou,W157-00-00      ,5637
      79     123     146     218
River Rch & RM=Buffalo Bayou,W157-00-00      ,3220
     119     184     219     327
River Rch & RM=Buffalo Bayou,W157-00-00      ,1721
     143     222     264     395
River Rch & RM=Buffalo Bayou,W157-00-00      ,119
     188     292     347     519
River Rch & RM=W157-00-00,W157-00-00      ,9231
      55      85     102     153
River Rch & RM=W157-00-00,W157-00-00      ,6442
      60      93     111     166
River Rch & RM=W157-00-00,W157-00-00      ,5637
      79     123     146     218
River Rch & RM=W157-00-00,W157-00-00      ,3220
     119     184     219     327
River Rch & RM=W157-00-00,W157-00-00      ,1721
     143     222     264     395
River Rch & RM=W157-00-00,W157-00-00      ,119
     188     292     347     519
Boundary for River Rch & Prof#=W157-00-00,W157-00-00      , 1
Up Type= 0
Dn Type= 3
Dn Slope=.004
Boundary for River Rch & Prof#=W157-00-00,W157-00-00      , 2
Up Type= 0
Dn Type= 3
Dn Slope=.004
Boundary for River Rch & Prof#=W157-00-00,W157-00-00      , 3
Up Type= 0
Dn Type= 3
Dn Slope=.004
Boundary for River Rch & Prof#=W157-00-00,W157-00-00      , 4
Up Type= 0
Dn Type= 3
Dn Slope=.004
DSS Import GetInterval= 0
DSS Import GetPeak= 0
DSS Import FillOption= 0

--- W157-00-00.g01 (geometry) ---

Geom Title=W157-00-00 June 2007
Version=Version 3.0.1  Mar 2001

River Reach=W157-00-00      ,W157-00-00
Reach XY= 30
     3059234.995    13831579.647     3059229.119    13831825.289
     3059199.652    13832593.705     3059191.228     13832937.98
      3059161.89    13833585.836     3059153.749    13833856.235
     3059134.444    13834313.632      3059117.71    13834630.363
     3059084.075     13835600.71     3059048.601    13836547.641
     3059047.628    13836614.021     3059010.552    13837600.994
     3058970.787    13838682.097     3058958.199    13838751.901
     3058946.872    13839017.191      3058938.46     13839447.08
     3058920.723    13839540.629     3058953.908    13839641.616
     3058939.032    13839747.466     3058927.875    13839834.721
     3058931.594    13839844.734     3058992.243    13839902.522
     3059057.625    13839943.122      3059115.11     13839988.11
     3059155.099    13840053.093     3059170.095    13840140.569
     3059140.103    13840258.037     3059048.029     13840355.39
     3058929.219    13840487.846     3058932.572    13840622.801

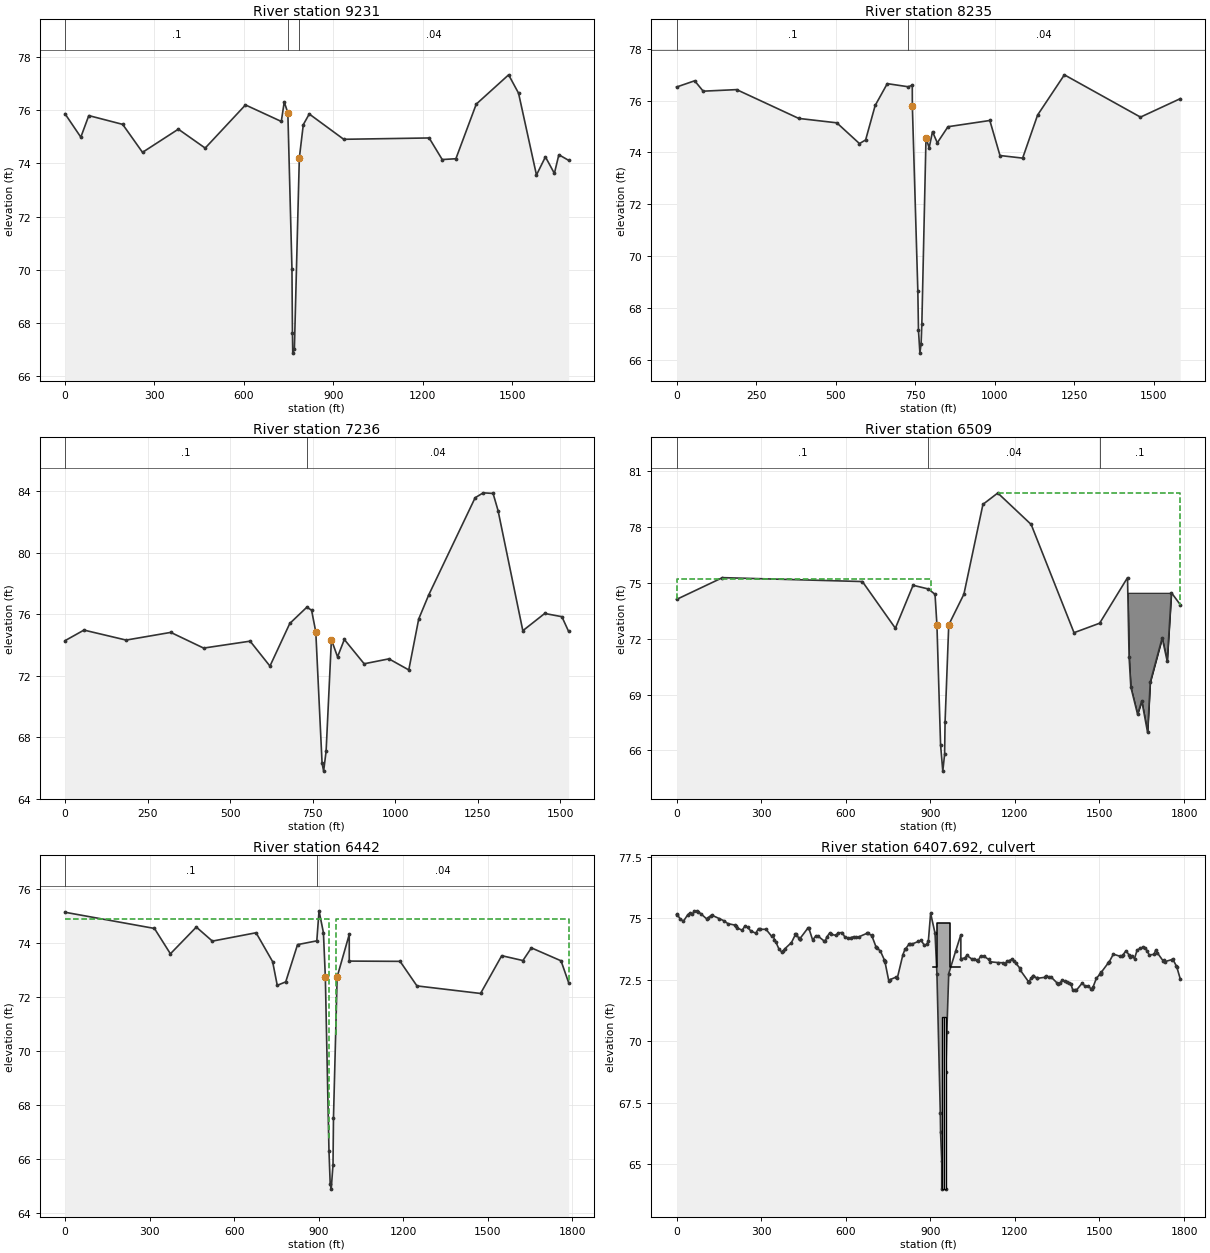
Type RM Length L Ch R = 1 ,9231    ,995.89,996.25,996.49
BEGIN DESCRIPTION:
Sta. 9231
END DESCRIPTION:
XS GIS Cut Line= 2
     3058469.136    13831560.883     3060156.755    13831637.593
#Sta/Elev= 30
       0   75.86   53.16   74.98    79.9   75.79  193.55   75.46  260.09   74.41
  380.21   75.28   470.3   74.57  605.44   76.19  725.57   75.57  735.44 76.3007
  747.55 75.8925  761.33 70.0367  762.92 67.6438  764.04 66.8729  769.51 67.0444
  786.06 74.1963  799.36 75.4503  819.31   75.85  934.98    74.9 1221.46   74.95
 1265.32   74.14 1311.17   74.17 1379.45   76.22 1488.08   77.32 1521.39   76.63
 1581.45   73.56 1611.48   74.24 1641.51   73.62 1656.53   74.32 1689.36   74.11
#Mann= 3 ,-1 , 0
       0      .1       0  747.55     .04       0  786.06     .04       0
Bank Sta=747.55,786.06
XS Rating Curve= 0
Exp/Cntr=.3,.1

Type RM Length L Ch R = 1 ,8235    ,998.99,998.77,998.55
BEGIN DESCRIPTION:
Sta. 8235
END DESCRIPTION:
XS GIS Cut Line= 2
     3058435.351    13832550.028     3060016.775    13832635.418
#Sta/Elev= 30
       0   76.52   56.87   76.76   83.72   76.36  188.88   76.42  384.16   75.31
  503.87   75.14  575.13   74.34  594.47   74.48  624.51   75.81  662.57   76.65
  728.51   76.53  741.18   76.59   741.4 75.7874  758.65 68.6645  760.68 67.1373
  765.15 66.2636  768.92 66.6317  771.23 67.3732  784.34 74.5671  794.23  74.176
  804.77    74.8   819.8   74.37  853.41   74.99  985.04   75.23 1016.95   73.88
 1088.22   73.78 1135.25   75.44 1219.42   76.99 1458.77   75.36 1583.73   76.07
#Mann= 2 ,-1 , 0
       0      .1       0  728.51     .04       0
Bank Sta=741.4,784.34
XS Rating Curve= 0
Exp/Cntr=.3,.1

Type RM Length L Ch R = 1 ,7236    ,727.69,727.61,727.89
BEGIN DESCRIPTION:
Sta. 7236
END DESCRIPTION:
XS GIS Cut Line= 2
     3058378.884    13833552.729     3059902.524    13833623.897
#Sta/Elev= 30
       0   74.27    57.5   74.96  185.27   74.31  320.42   74.81  419.94   73.79
  560.68   74.24  620.75   72.62  680.81   75.39  732.14   76.44  746.72   76.26
  759.58 74.8378  778.58 66.3107  783.32 65.7936  790.85 67.1005  806.86 74.3364
  825.48   73.22  845.99   74.35  906.06   72.77  981.14   73.09  1041.2   72.37
 1071.24   75.68 1101.27   77.23 1242.12   83.56 1266.54   83.88 1296.48   83.84
  1311.5   82.73 1386.58   74.92 1452.87   76.04 1504.82   75.83  1525.3   74.87
#Mann= 2 ,-1 , 0
       0      .1       0  732.14     .04       0
Bank Sta=759.58,806.86
XS Rating Curve= 0
Exp/Cntr=.3,.1

Type RM Length L Ch R = 1 ,6509    ,66.71,66.71,66.85
BEGIN DESCRIPTION:
Sta. 6509: edited bank stations
END DESCRIPTION:
XS GIS Cut Line= 3
     3058191.331    13834264.653     3059134.172     13834316.37
     3059975.111    13834362.498
#Sta/Elev= 30
       0   74.12  162.87   75.29   659.1   75.08  776.07   72.57  838.88   74.88
  893.23   74.68  916.75 74.3921  923.53 72.7346  936.38  66.312  944.29 64.8875
  950.72 65.7945  952.37 67.5372  965.39 72.7548 1019.15    74.4  1086.7   79.23
 1139.33   79.84  1257.7   78.15 1409.74   72.33 1500.63   72.84  1599.5   75.29
 1605.03   71.04 1611.21   69.41 1635.08   67.95  1650.1   68.66  1670.7   66.97
 1680.14   69.67 1722.47   72.05 1740.23    70.8 1755.26   74.48 1786.46   73.84
#Mann= 3 ,-1 , 0
       0      .1       0  893.23     .04       0 1500.63      .1       0
#XS Ineff= 2 , 0
       0     901    75.2    1140       0   79.85
Permanent Ineff=
       F       F
#Block Obstruct= 1 ,-1
    1580 1755.26   74.48
Bank Sta=923.53,965.39
XS Rating Curve= 0
Exp/Cntr=.5,.3

Type RM Length L Ch R = 1 ,6442    ,63.19,63.15,63.22
Node Photo=F:\TSARP\Field-Survey\W157-00-00\PHOTOS\W157-00-S1\W157-00-S1p1.JPG
BEGIN DESCRIPTION:
Sta. 6442: surveyed section copied from River Station 6509
channel slope is 0, therefore, elevations were not adjusted
END DESCRIPTION:
XS GIS Cut Line= 3
     3058187.139    13834337.849      3059129.98    13834389.566
      3059970.92    13834435.693
#Sta/Elev= 30
       0   75.15  317.29   74.55  373.98   73.61  465.88    74.6  522.85   74.08
  677.83   74.39  736.47   73.32  752.95   72.44  782.99   72.57   824.9   73.95
  893.23   74.09  901.11 75.2027  916.75 74.3921  923.53 72.7346  936.38  66.312
  940.79 65.0622  944.29 64.8875  950.72 65.7945  952.37 67.5372  965.39 72.7548
 1008.32 74.3282 1008.33   73.34  1188.6   73.33 1248.44   72.42 1474.03   72.14
 1549.14   73.54 1624.25   73.36  1654.3   73.83 1759.46   73.35 1786.46   72.54
#Mann= 2 ,-1 , 0
       0      .1       0  893.23     .04       0
#XS Ineff= 2 , 0
       0   935.5    74.9     960       0    74.9
Permanent Ineff=
       F       F
Bank Sta=923.53,965.39
XS Rating Curve= 0
Exp/Cntr=.5,.3

Type RM Length L Ch R = 2 ,6407.692,,,
BEGIN DESCRIPTION:
Culvert @ Del Monte (Structure 1)
END DESCRIPTION:
Bridge Culvert--1,0,-1,-1, 0
Deck Dist Width WeirC Skew NumUp NumDn MinLoCord MaxHiCord MaxSubmerge Is_Ogee
5,56.4,2.6,0, 6, 6, , , .95, 0, 0,0,,
     910   924.5   924.5   970.8   970.8    1006
      73      73    74.8    74.8      73      73
       0       0       0       0       0       0
     910   924.5   924.5   970.8   970.8    1006
      73      73    74.8    74.8      73      73
       0       0       0       0       0       0
BR Coef=-1 , 0 , 0 ,1.25, 0 ,,,.8,0,2,1,
WSPro=,,,, 1 ,,,, 0 ,,,, 0 ,,,,-1 ,-1 ,-1 , 0 , 0 , 0 , 0 , 0
Culvert=2,7,7,56.4,.013,.5,1,10,1,64,944,64,944,Culvert #1  , 0 ,5
Culvert Bottom n=.04
Culvert=2,7,7,56.4,.013,.5,1,10,1,64,951.5,64,951.5,Culvert #2  , 0 ,5
Culvert Bottom n=.04
Culvert Bottom Depth=2
BR U #Sta/Elev= 188
       0   75.15    1.82   75.16   12.74   74.97    24.4   74.88    40.2   75.15
   46.89    75.2   56.09   75.16   61.91   75.28   71.99    75.3   76.93   75.25
   85.36   75.19  106.98   74.97  109.85      75     122   75.11  125.97   75.12
  152.04   74.98  167.35    74.9  182.09   74.78  207.19   74.72   210.8    74.7
  215.03   74.61  232.73   74.51  242.18   74.68  252.26   74.63  262.72   74.49
  280.74   74.39  290.77   74.58  294.51   74.55  317.29   74.55  337.71   74.26
  342.39    74.3  347.34   74.13  351.95   74.04  362.36   73.77  373.98   73.61
  377.38   73.66  383.18   73.75  407.43   74.01  421.66   74.34  422.45   74.34
  423.16   74.32  436.03   74.18   437.4   74.17  437.47   74.17  437.56   74.17
  465.88    74.6  469.34   74.59  482.54   74.12  494.36   74.28  501.13   74.28
  522.85   74.08  527.61   74.08  532.92   74.24  542.63   74.39  548.82   74.35
  565.57    74.3   572.7    74.4   587.7   74.42   596.5   74.24  608.29    74.2
  617.74   74.21  628.29   74.25  636.78   74.23  647.79   74.25  673.88   74.38
  677.83   74.39  691.87    74.3  692.85   74.28  707.76   73.82  707.98   73.82
   709.9    73.8   722.9   73.67  736.47   73.32  737.92   73.26  739.55   73.21
  752.95   72.44  755.44    72.5  779.19   72.61  782.99   72.57  802.84   73.52
  810.28   73.74  813.04   73.77   824.9   73.95  828.06   73.95  834.92   73.95
   858.1   74.06   866.7    74.1  878.88   73.91  888.15   73.94  893.23   74.09
  901.11    75.2  916.75   74.39  923.53   72.73  935.43    67.1  936.38   66.31
   940.5   65.14   940.5      64     955      64     955   68.74  958.56   70.37
  965.39   72.75  989.49   73.65 1008.32   74.33 1008.33   73.34 1009.75   73.34
 1023.35    73.4 1029.61   73.49 1047.64   73.34  1053.4   73.33 1064.02   73.29
 1068.42   73.25 1078.26   73.46 1089.23   73.46 1106.74   73.33 1113.49   73.23
 1139.04    73.2 1158.55   73.19 1163.71   73.13 1173.58   73.27 1178.93   73.27
  1188.6   73.33 1197.75   73.25 1203.62   73.17 1216.38   72.99 1218.64    72.9
 1247.59   72.43 1248.44   72.42 1249.16   72.42 1257.65   72.56  1263.4   72.65
 1264.06   72.66 1278.73   72.57 1279.96   72.56 1306.12    72.6 1308.78   72.64
 1320.36   72.62 1327.64   72.62 1348.85   72.38 1353.85   72.34 1359.43   72.38
 1368.87   72.48 1377.33   72.45 1383.89    72.4 1391.57   72.35 1398.91   72.32
 1405.81   72.07 1413.94    72.1 1418.34   72.08 1439.01   72.37 1448.54   72.24
 1459.01   72.25 1470.69   72.13 1474.03   72.14 1477.02    72.2 1489.05   72.56
 1502.48   72.74 1504.07   72.75 1504.81   72.77 1506.79   72.81 1531.52   73.19
 1534.12   73.22 1534.27   73.22 1549.14   73.54 1574.47   73.45 1579.19   73.47
 1581.95   73.49 1594.21   73.68 1605.19   73.51 1609.23   73.44 1613.74   73.48
 1624.25   73.36 1633.67   73.71 1645.53   73.78  1654.3   73.83 1661.42    73.8
 1669.32   73.67  1676.4   73.51 1693.21   73.53 1699.37    73.7 1704.88    73.6
    1725   73.28 1729.41   73.29 1733.36   73.24 1756.79   73.32 1759.46   73.35
 1772.68   73.06 1774.48   73.01 1786.46   72.54
BR U #Mann= 2
       0      .1  893.23     .04
BR D #Sta/Elev= 190
       0   74.79    2.67   74.78   20.39   74.62   31.16   74.48   37.73    74.3
   50.44   74.18   53.17   74.19   88.12   74.25   91.71    74.3   99.51    74.3
  110.53   74.21  120.96   74.33  125.55   74.39  135.54   74.16  140.57    74.1
  149.15   73.83  164.82   73.72  170.62   73.76  183.22   74.03  187.81    74.1
  200.66   73.95  202.05   73.93  215.69   73.62  227.37   73.95  230.54   74.04
   230.8   74.05  245.73   74.23  259.86   73.88  262.69   73.82   287.5   73.46
   290.8   73.47  294.48   73.44  305.82    73.6  315.98   73.45  320.84   73.45
  332.36   73.37  350.89   73.38   354.9   73.17  358.71   73.25  372.14   73.14
  395.96   73.21  401.43   73.17  410.98    73.1  421.63   73.11     426   73.17
  450.48   73.07  456.05   73.06   458.4   73.06  471.07   73.04  472.64   73.01
  501.11   72.93  501.13   72.93  501.25   72.93   528.2   73.12  531.16   73.16
   532.9   73.13  558.09   73.13   561.2   73.16  572.33   73.03  576.23   72.92
  595.89   72.99  606.27   73.11  615.05   72.99  621.29   72.76  628.26   72.66
  643.53   72.58  660.05   72.47  666.36   72.42  672.02   72.44  691.84   72.82
   700.5   72.82  711.43   72.83  714.74   72.82  726.45   72.85  739.52   72.55
  741.47   72.52  755.42   72.32  757.47   72.35  771.52   72.55  785.95   72.29
  786.54   72.28  800.19   72.88   803.1      73  816.59   73.29     819   73.34
  831.61   73.46  834.89   73.51  846.63   73.46  857.16   73.54  875.23   73.62
  888.59   73.57   891.7   73.79  893.23    73.8  899.88   73.87  916.75   74.39
  923.53   72.73  935.43    67.1  936.38   66.31   940.5   65.14   940.5      64
     955      64     955   68.74  958.56   70.37  965.39   72.75  989.49   73.65
 1018.56   73.27  1026.9   73.32 1041.52   73.39 1041.93    73.4 1042.62   73.39
 1056.53   73.54 1081.62   73.17 1085.98   73.25 1086.99   73.18 1099.26   73.15
 1105.09    73.2 1127.74   73.12 1132.06   73.14 1136.88   73.16 1147.08   73.21
 1156.22   73.14 1176.05   73.02 1184.57    73.1 1192.15   73.06 1200.46   73.05
 1213.19   73.09 1232.25   73.08 1237.22    73.1 1241.67    73.1 1264.04   72.97
 1267.26   72.94 1294.16   72.79 1297.31   72.79 1298.64   72.82 1312.33   72.74
 1322.86   72.79 1327.35   72.83 1341.36   72.71 1342.38   72.73 1343.51    72.7
  1357.4   72.81  1359.4   72.72 1372.42   72.58  1375.3   72.52 1398.33    72.2
 1402.47   72.11 1407.09      72 1417.49   72.05 1422.98   72.11 1441.05    72.2
 1451.05   72.14 1462.56    72.1 1470.66   72.21 1483.78   72.23  1492.6   72.63
 1502.45   73.14 1507.62   73.32 1512.26   73.34 1522.65   73.49 1529.97   73.48
 1546.56   73.43 1552.69   73.37 1566.03   73.09 1567.71   73.11 1569.22   73.17
 1596.74   73.72 1597.71   73.75 1597.76   73.75 1597.82   73.75 1626.19   74.08
  1627.8   74.05 1629.61   74.05 1642.83   74.01  1645.5      74 1657.85   74.11
 1668.91   74.22 1672.87   74.25 1675.02   74.24 1696.09   74.14 1713.64   73.98
 1717.94   74.01 1722.02   73.97 1732.96   74.27 1744.53   74.12 1747.98   74.14
 1754.36      74 1772.66   74.07 1778.03   73.94 1782.84   73.91 1786.46    73.9
BR D #Mann= 2
       0      .1  893.23     .04
BC Design=,, 0 ,, 0 ,,,,,,

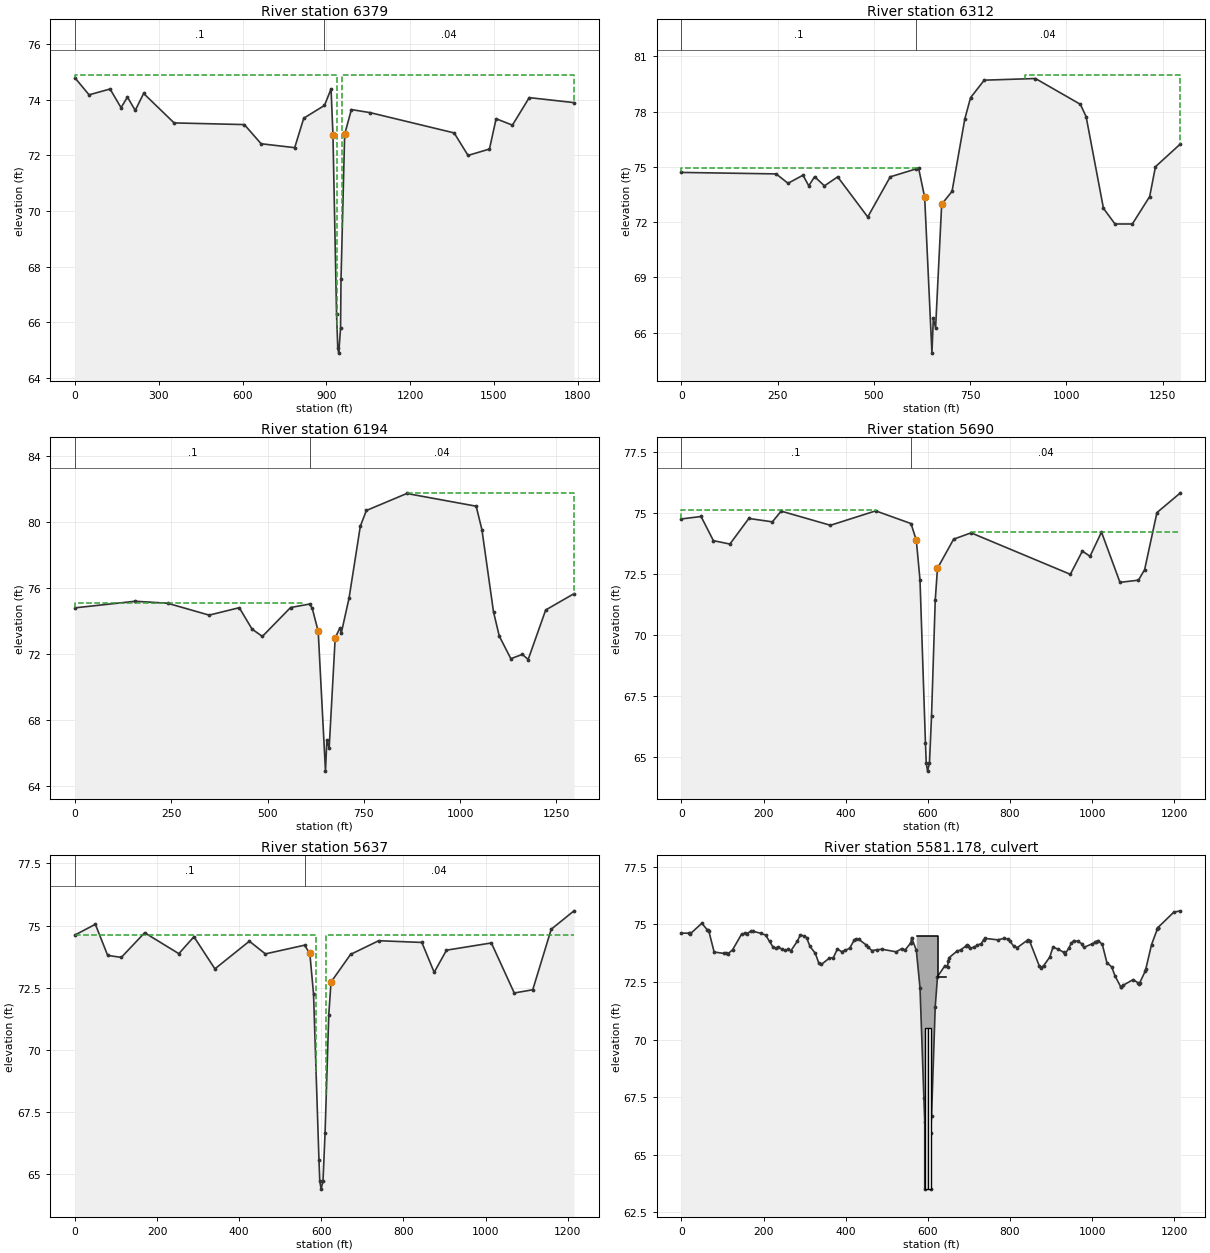
Type RM Length L Ch R = 1 ,6379    ,68.51,67.42,66.73
Node Photo=F:\TSARP\Field-Survey\W157-00-00\PHOTOS\W157-00-S1\W157-00-S1p8.JPG
BEGIN DESCRIPTION:
Sta. 6379: surveyed section copied from River Station 6509
channel slope is 0, therefore, elevations were not adjusted
END DESCRIPTION:
XS GIS Cut Line= 3
     3058183.592    13834394.277     3059126.433    13834445.994
     3059967.373    13834492.122
#Sta/Elev= 30
       0   74.79   50.44   74.18  125.55   74.39  164.82   73.72  187.81    74.1
  215.69   73.62  245.73   74.23   354.9   73.17  606.27   73.11  666.36   72.42
  786.54   72.28     819   73.34  893.23    73.8  916.75 74.3921  923.53 72.7346
  936.38  66.312  940.79 65.0622  944.29 64.8875  950.72 65.7945  952.37 67.5372
  965.39 72.7548  989.49 73.6501 1056.53   73.54  1357.4   72.81 1407.09      72
 1483.78   72.23 1507.62   73.32 1566.03   73.09 1626.19   74.08 1786.46    73.9
#Mann= 2 ,-1 , 0
       0      .1       0  893.23     .04       0
#XS Ineff= 2 , 0
       0   938.5    74.9     957       0    74.9
Permanent Ineff=
       F       F
Bank Sta=923.53,965.39
XS Rating Curve= 0
Exp/Cntr=.5,.3

Type RM Length L Ch R = 1 ,6312    ,117.91,117.42,117.53
BEGIN DESCRIPTION:
Sta. 6312: surveyed section copied from River Station 6194
channel slope is 0, therefore, elevations were not adjusted
END DESCRIPTION:
XS GIS Cut Line= 3
     3058473.385    13834495.058     3059123.634    13834513.364
     3059768.878    13834531.528
#Sta/Elev= 30
       0    74.7  245.91   74.62   276.8   74.11  315.69   74.55   330.7   73.97
  345.71   74.47  371.33   73.97  405.73   74.46  483.82   72.28   542.2   74.46
  609.12   74.89  615.81   74.94  631.66  73.352  650.55 64.8865  654.15 66.7683
  660.07 66.2615  675.84 72.9722  702.74   73.67  735.86    77.6  750.87   78.76
  786.34   79.71  919.33    79.8 1035.98    78.4 1050.99   77.73    1096   72.75
 1125.99    71.9 1171.03    71.9 1216.05   73.39 1231.06   75.01 1296.01   76.25
#Mann= 2 ,-1 , 0
       0      .1       0  609.12     .04       0
#XS Ineff= 2 , 0
       0   615.5   74.95   892.5       0      80
Permanent Ineff=
       F       F
Bank Sta=631.66,675.84
XS Rating Curve= 0
Exp/Cntr=.3,.1

Type RM Length L Ch R = 1 ,6194    ,503.8,503.6,503.98
BEGIN DESCRIPTION:
Sta. 6194
END DESCRIPTION:
XS GIS Cut Line= 3
     3058467.449    13834612.329     3059117.698    13834630.635
     3059762.942      13834648.8
#Sta/Elev= 30
       0   74.78  156.57   75.18  240.28   75.06  348.45   74.34  426.67   74.79
  459.92   73.49   486.7   73.05   559.9    74.8  609.12   75.01  616.31 74.7453
  631.66  73.352  650.55 64.8865  654.15 66.7683  660.07 66.2615  675.84 72.9722
  688.04 73.5573  691.76   73.27  711.79   75.37  741.07   79.73   756.8   80.68
  861.85   81.71 1041.92   80.94 1056.92   79.51 1086.94   74.54 1101.94   73.07
 1131.95    71.7 1161.97   71.96 1176.97   71.65 1222.47   74.65 1296.01   75.64
#Mann= 2 ,-1 , 0
       0      .1       0  609.12     .04       0
#XS Ineff= 2 , 0
       0     596    75.1     862       0   81.75
Permanent Ineff=
       F       F
Bank Sta=631.66,675.84
XS Rating Curve= 0
Exp/Cntr=.3,.1

Type RM Length L Ch R = 1 ,5690    ,53.23,53.21,53.21
BEGIN DESCRIPTION:
Sta. 5690: edited bank stations
END DESCRIPTION:
XS GIS Cut Line= 3
     3058501.199    13835118.954     3059100.308    13835133.932
     3059716.235     13835149.33
#Sta/Elev= 30
       0   74.75   47.77   74.85   77.78   73.86  117.96   73.72  164.13   74.77
  221.45   74.63  242.83   75.07  362.87   74.49  473.09   75.08  559.09   74.56
  572.02  73.878  581.01 72.2507  594.27 65.5705  596.25 64.7343  599.44  64.412
  604.06 64.7351  609.09 66.6652  618.13 71.4203  623.62 72.7295  662.96   73.92
   705.4   74.18  947.16   72.48  976.43   73.43  995.16   73.22 1023.07   74.21
 1068.09   72.15  1113.1   72.24 1128.11   72.67 1158.12   75.01 1215.42   75.82
#Mann= 2 ,-1 , 0
       0      .1       0  559.09     .04       0
#XS Ineff= 2 , 0
       0     473    75.1     705       0    74.2
Permanent Ineff=
       F       F
Bank Sta=572.02,623.62
XS Rating Curve= 0
Exp/Cntr=.5,.3

Type RM Length L Ch R = 1 ,5637    ,113.19,113.15,113.15
Node Photo=F:\TSARP\Field-Survey\W157-00-00\PHOTOS\W157-00-S2\W157-00-S2p1.JPG
BEGIN DESCRIPTION:
Sta. 5637: surveyed section copied from River Station 5690
channel slope is 0, therefore, elevations were not adjusted
END DESCRIPTION:
XS GIS Cut Line= 4
     3058499.365    13835172.131     3059098.473    13835187.109
       3059714.4    13835202.507 3059714.410006613835202.5072502
#Sta/Elev= 30
       0   74.62    49.6   75.05   79.61    73.8  112.85   73.72  169.64   74.71
  252.95   73.87  289.68   74.55  340.78   73.26  424.72   74.37  463.74   73.86
  559.09   74.21  572.02  73.878  581.01 72.2507  594.27 65.5705  596.25 64.7343
  599.44  64.412  604.06 64.7351  609.09 66.6652  618.13 71.4203  623.62 72.7295
  671.21   73.84  739.82   74.39  844.85   74.32  874.86   73.12  904.87   74.01
 1014.16    74.3 1069.92   72.29 1114.94   72.42 1159.95   74.85 1215.42   75.59
#Mann= 2 ,-1 , 0
       0      .1       0  559.09     .04       0
#XS Ineff= 2 , 0
       0   587.5    74.6     612       0    74.6
Permanent Ineff=
       F       F
Bank Sta=572.02,623.62
XS Rating Curve= 0
Exp/Cntr=.5,.3

Type RM Length L Ch R = 2 ,5581.178,,,
BEGIN DESCRIPTION:
Culvert @ Briar Forest (Structure 2)
END DESCRIPTION:
Bridge Culvert--1,0,-1,-1, 0
Deck Dist Width WeirC Skew NumUp NumDn MinLoCord MaxHiCord MaxSubmerge Is_Ogee
5,91,2.6,0, 4, 4, , , .95, 0, 0,0,,
     573     624     624     645
    74.5    74.5    72.7    72.7
       0       0       0       0
     573     624     624     645
    74.5    74.5    72.7    72.7
       0       0       0       0
BR Coef=-1 , 1 , 1 ,1.25, 0 ,,,.8,0,2,0,
WSPro=,,,, 1 ,,,, 0 ,,,, 0 ,,,,-1 ,-1 ,-1 , 0 , 0 , 0 , 0 , 0
Multiple Barrel Culv=2,7,7,91,.013,.2,1,10,2,63.5,63.5, 2,Culvert #1  , 0 ,5
     596     596   603.5   603.5
Culvert Bottom n=.013
BR U #Sta/Elev= 128
       0   74.62    17.9   74.62    19.6   74.61   21.47   74.59    49.6   75.05
   62.64   74.77   64.61   74.74   66.68   74.71   79.61    73.8  103.64   73.74
  108.07   73.74  112.85   73.72  124.63    73.9  146.51   74.58  154.64   74.61
  159.01    74.6  169.64   74.71   174.4    74.7  194.39   74.61  205.18   74.53
  214.66   74.26  223.67      74  229.66   73.96  235.96   74.02  244.67   73.92
  252.95   73.87  259.67   73.91  266.74   73.86  282.22   74.27  289.68   74.55
  297.52    74.5  304.68   74.43  312.91   74.05  326.14   73.74  334.69   73.31
  340.78   73.26  359.08   73.52  370.06   73.56  379.71   73.93  389.86   73.82
  399.33   73.87  409.72   73.97  420.63   74.31  424.72   74.37  432.31   74.35
  448.92   74.12  454.73   74.02  463.74   73.86  475.89    73.9  488.66   73.92
  523.02   73.81  536.66   73.95  544.76   73.89  559.09   74.21  559.14   74.21
  560.41   74.43  572.02   73.88  581.01   72.25  590.27   67.48   592.5   66.42
   592.5    63.5     607    63.5     607   65.92  609.09   66.67  618.13   71.42
  623.62   72.73  641.82   73.21  648.19   73.17  649.79   73.39  651.48   73.55
  671.21   73.84   679.8   73.89  692.11   74.05  694.81    74.1  697.64   74.08
   703.8   73.97  713.03   74.01  720.95    74.1  730.49   74.17  736.02   74.34
  739.82   74.39  770.83   74.33  784.83   74.39  794.58   74.37  799.84   74.27
  809.22   74.06  817.76   73.99  841.63    74.3  844.85   74.32  848.15   74.27
  871.27   73.21  874.86   73.12  882.32   73.21  897.05   73.58  904.87   74.01
  918.18   73.92  930.55   73.79  934.88   73.72  943.87   73.99  949.89   74.19
   955.6    74.3  964.89   74.26  974.65   74.17   979.9      74 1000.72   74.16
  1007.7   74.22  1009.9   74.25 1014.16    74.3 1024.91   74.14 1036.21   73.34
 1048.11   73.15 1055.99   72.76 1069.92   72.29 1071.34   72.29 1075.37   72.35
 1099.93    72.6 1113.16   72.45 1114.94   72.42 1115.79   72.45 1129.94   72.98
 1131.27   73.08 1144.95   74.12 1159.33   74.82 1159.64   74.83 1159.95   74.85
 1160.35   74.86 1199.04   75.53 1215.42   75.59
BR U #Mann= 2
       0      .1  559.09     .04
BR D #Sta/Elev= 119
       0   72.94   14.75   72.99   23.61   72.87   32.91    72.8   44.03   72.85
   53.61   72.94    82.8   73.12   95.01   73.15  104.17   73.18  113.63   73.28
  125.25   73.19  134.93   73.16  158.65   73.34  171.42   73.29  184.86   73.02
  190.42   73.01  217.59   73.27  218.67   73.26  219.69   73.26  233.67   73.24
  248.37   73.15  248.97   73.14   260.8   72.78  263.65    72.7  263.75    72.7
  278.69   72.85  279.14   72.85  293.69   72.76  295.42   72.74   316.9   72.92
   323.7   72.83   336.8   72.75   338.7   72.78  351.44   72.87  353.71   72.88
  366.08   73.14  371.48    73.1  383.72   73.02  392.87   73.21  404.43   73.32
  413.73   73.39  424.64   73.26  428.73   73.25  439.28    73.3  448.43   73.39
  458.74   73.56  468.55   73.65  473.75   73.76  479.21   73.78  493.35   73.86
  503.76    73.7  514.43    73.7  527.11   73.66  540.76   73.39  559.09   73.33
  560.41   74.43  572.02   73.88  581.01   72.25  590.27   67.48   592.5   66.42
   592.5    63.5     607    63.5     607   65.92  609.09   66.67  618.13   71.42
  623.62   72.73  641.82   73.21  644.22   72.92   653.8   73.26  658.86   73.24
  679.27   73.11  683.81   73.03  688.13   72.94  704.36   72.77  732.05   72.76
  743.83   72.67  756.22   72.59  758.84   72.56   763.7   72.55  788.84   72.68
  802.38   72.41  816.64   72.29  819.88   72.29  848.55   72.11  848.86   72.12
  849.16   72.11  860.98   72.04  891.58    71.9  893.88   71.86  895.61   71.83
  917.09   71.76  923.89   71.78  930.52   71.95  938.89   71.94  945.34   71.96
  962.67   72.17   968.9   72.33  992.34   72.64  998.91   72.71 1010.19   72.82
 1013.91   72.85 1024.82   72.82 1031.05   72.89 1037.76   72.87 1058.93   72.58
  1063.9   72.62 1078.08    72.6 1094.78   72.68 1103.94   72.67 1116.73   72.71
 1133.95   72.77 1149.53   72.88 1163.96   72.86 1171.73   72.83 1185.85   72.97
 1202.51   72.87 1208.98   72.78 1215.13   72.81 1215.42   72.81
BR D #Mann= 2
       0      .1  559.09     .04
BC Design=,, 0 ,, 0 ,,,,,,

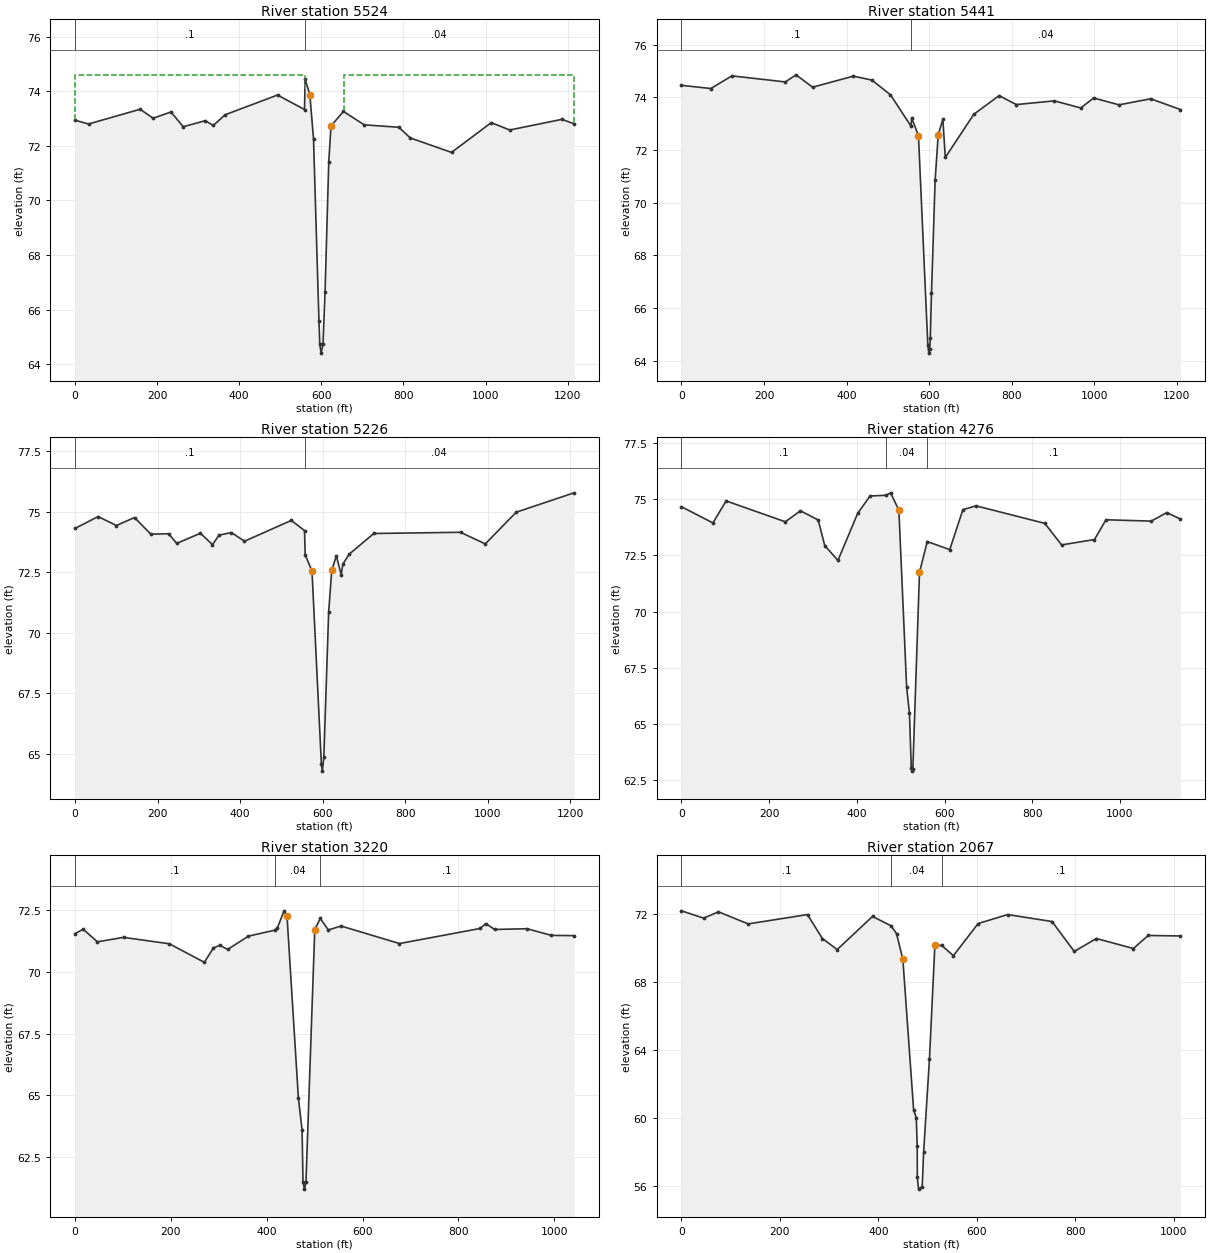
Type RM Length L Ch R = 1 ,5524    ,82.73,82.75,82.8
Node Photo=F:\TSARP\Field-Survey\W157-00-00\PHOTOS\W157-00-S2\W157-00-S2p8.JPG
BEGIN DESCRIPTION:
Sta. 5524: surveyed section copied from River Station 5690
channel slope is 0, therefore, elevations were not adjusted
END DESCRIPTION:
XS GIS Cut Line= 4
     3058495.356    13835285.212     3059094.464     13835300.19
     3059710.391    13835315.588 3059710.401006613835315.5882502
#Sta/Elev= 30
       0   72.94   32.91    72.8  158.65   73.34  190.42   73.01  233.67   73.24
  263.65    72.7   316.9   72.92   336.8   72.75  366.08   73.14  493.35   73.86
  559.09   73.33  560.41 74.4347  572.02  73.878  581.01 72.2507  594.27 65.5705
  596.25 64.7343  599.44  64.412  604.06 64.7351  609.09 66.6652  618.13 71.4203
  623.62 72.7295   653.8   73.26  704.36   72.77  788.84   72.68  816.64   72.29
  917.09   71.76 1013.91   72.85 1058.93   72.58 1185.85   72.97 1215.42   72.81
#Mann= 2 ,-1 , 0
       0      .1       0  559.09     .04       0
#XS Ineff= 2 , 0
       0     560    74.6     654       0    74.6
Permanent Ineff=
       F       F
Bank Sta=572.02,623.62
XS Rating Curve= 0
Exp/Cntr=.5,.3

Type RM Length L Ch R = 1 ,5441    ,215.92,215.73,215.74
BEGIN DESCRIPTION:
Sta. 5441: surveyed section copied from River Station 5226
channel slope is 0, therefore, elevations were not adjusted
END DESCRIPTION:
XS GIS Cut Line= 3
     3058492.686    13835366.855     3059091.627    13835382.896
     3059701.305    13835399.225
#Sta/Elev= 30
       0   74.46   71.29   74.34  122.11   74.82  251.78   74.59  277.59   74.86
  317.75   74.39  416.42   74.81  461.43   74.66  506.45    74.1  556.16   72.91
  557.78 73.2237  574.27 72.5419  596.97 64.5732  599.25  64.282  601.36 64.4274
   602.9 64.8489  605.81 66.5688  614.62 70.8551  622.12 72.5894  633.35 73.1719
  639.26   71.72  708.34   73.36  769.63   74.07  811.29   73.73  903.49   73.87
  967.65    73.6  998.48   73.98 1060.16   73.72 1136.96   73.95 1209.05   73.54
#Mann= 2 ,-1 , 0
       0      .1       0  556.16     .04       0
Bank Sta=574.27,622.12
XS Rating Curve= 0
Exp/Cntr=.3,.1

Type RM Length L Ch R = 1 ,5226    ,950.77,950.08,949.83
BEGIN DESCRIPTION:
Sta. 5226
END DESCRIPTION:
XS GIS Cut Line= 3
     3058485.209    13835582.459     3059084.151      13835598.5
     3059693.829    13835614.828
#Sta/Elev= 30
       0   74.31   55.99    74.8  100.37   74.43  144.21   74.76  183.81   74.07
  226.69   74.09  246.51   73.69  303.85   74.11  333.16   73.64  348.87   74.03
  378.88   74.14  410.61   73.78  524.17   74.64  556.16   74.22  557.78 73.2237
  574.27 72.5419  596.97 64.5732  599.25  64.282   602.9 64.8489  614.62 70.8551
  622.12 72.5894  633.35 73.1719  644.98    72.4  648.98   72.83  663.98   73.24
     724    74.1  934.08   74.15   994.1   73.67 1069.13   74.98 1209.05   75.78
#Mann= 2 ,-1 , 0
       0      .1       0  556.16     .04       0
Bank Sta=574.27,622.12
XS Rating Curve= 0
Exp/Cntr=.3,.1

Type RM Length L Ch R = 1 ,4276    ,1055.62,1055.41,1055.3
BEGIN DESCRIPTION:
Sta. 4276
END DESCRIPTION:
XS GIS Cut Line= 2
     3058522.152     13836538.99     3059660.077    13836558.277
#Sta/Elev= 30
       0   74.67   71.81   73.95  101.82   74.93  236.84      74  271.41   74.49
  311.85   74.08  326.85   72.94  356.85   72.28  401.86   74.37  430.05   75.15
  466.62   75.18  476.87   75.29  495.87 74.5174  513.59  66.632  519.95 65.4875
   524.2 63.0235  525.88 62.8942  527.67 62.9743   542.9  71.746  560.61 73.1199
  611.89   72.76  641.89   74.54   671.9   74.71  828.77   73.93  866.93   72.97
  941.94   73.21  968.27   74.09 1071.54   74.03 1106.96   74.41 1138.09   74.12
#Mann= 3 ,-1 , 0
       0      .1       0  466.62     .04       0  560.61      .1       0
Bank Sta=495.87,542.9
XS Rating Curve= 0
Exp/Cntr=.3,.1

Type RM Length L Ch R = 1 ,3220    ,1150.46,1153.48,1156.72
BEGIN DESCRIPTION:
Sta. 3220
END DESCRIPTION:
XS GIS Cut Line= 2
     3058532.051      13837595.6      3059572.98    13837610.863
#Sta/Elev= 30
       0   71.55    16.9   71.73   46.91   71.22  101.21    71.4  196.92   71.14
  269.76   70.39  288.83   70.97  301.94   71.08   318.4   70.91  361.94   71.45
  416.42   71.69  421.95   71.77   436.2 72.4746  442.34 72.2573  466.04 64.8986
  473.74 63.6034  475.68 61.4966  478.73  61.206  481.87 61.4978  500.22  71.715
  511.65 72.1654  528.58    71.7  554.96   71.86  676.98   71.15  845.12   71.76
     857   71.96  875.35   71.72  943.16   71.75  993.89   71.48 1041.04   71.47
#Mann= 3 ,-1 , 0
       0      .1       0  416.42     .04       0  511.65      .1       0
Bank Sta=442.34,500.22
XS Rating Curve= 0
Exp/Cntr=.3,.1

Type RM Length L Ch R = 1 ,2067    ,266.03,262.43,260.1
BEGIN DESCRIPTION:
Sta. 2067
END DESCRIPTION:
XS GIS Cut Line= 4
     3058474.052     13838709.79       3058960.7    13838754.478
     3059039.516    13838763.281     3059484.455    13838783.052
#Sta/Elev= 30
       0   72.18   45.09   71.75   75.22   72.12  135.47   71.41  255.97   71.96
   286.1   70.55  316.23    69.9  387.99   71.85  425.62    71.3  436.73   70.84
  449.61  69.325  471.52 60.4438  476.85 59.9992  478.78  58.335  479.03 56.4832
  481.44 55.7914  488.91 55.9322  491.81 57.9802  503.65 63.4656  514.63 70.1451
  528.52 70.1411  552.24   69.54  602.47   71.43  662.53   71.96  752.62   71.55
  797.67   69.79  842.71   70.55  917.78   69.96  947.81   70.73 1013.38    70.7
#Mann= 3 ,-1 , 0
       0      .1       0  425.62     .04       0  528.52      .1       0
Bank Sta=449.61,514.63
XS Rating Curve= 0
Exp/Cntr=.3,.1