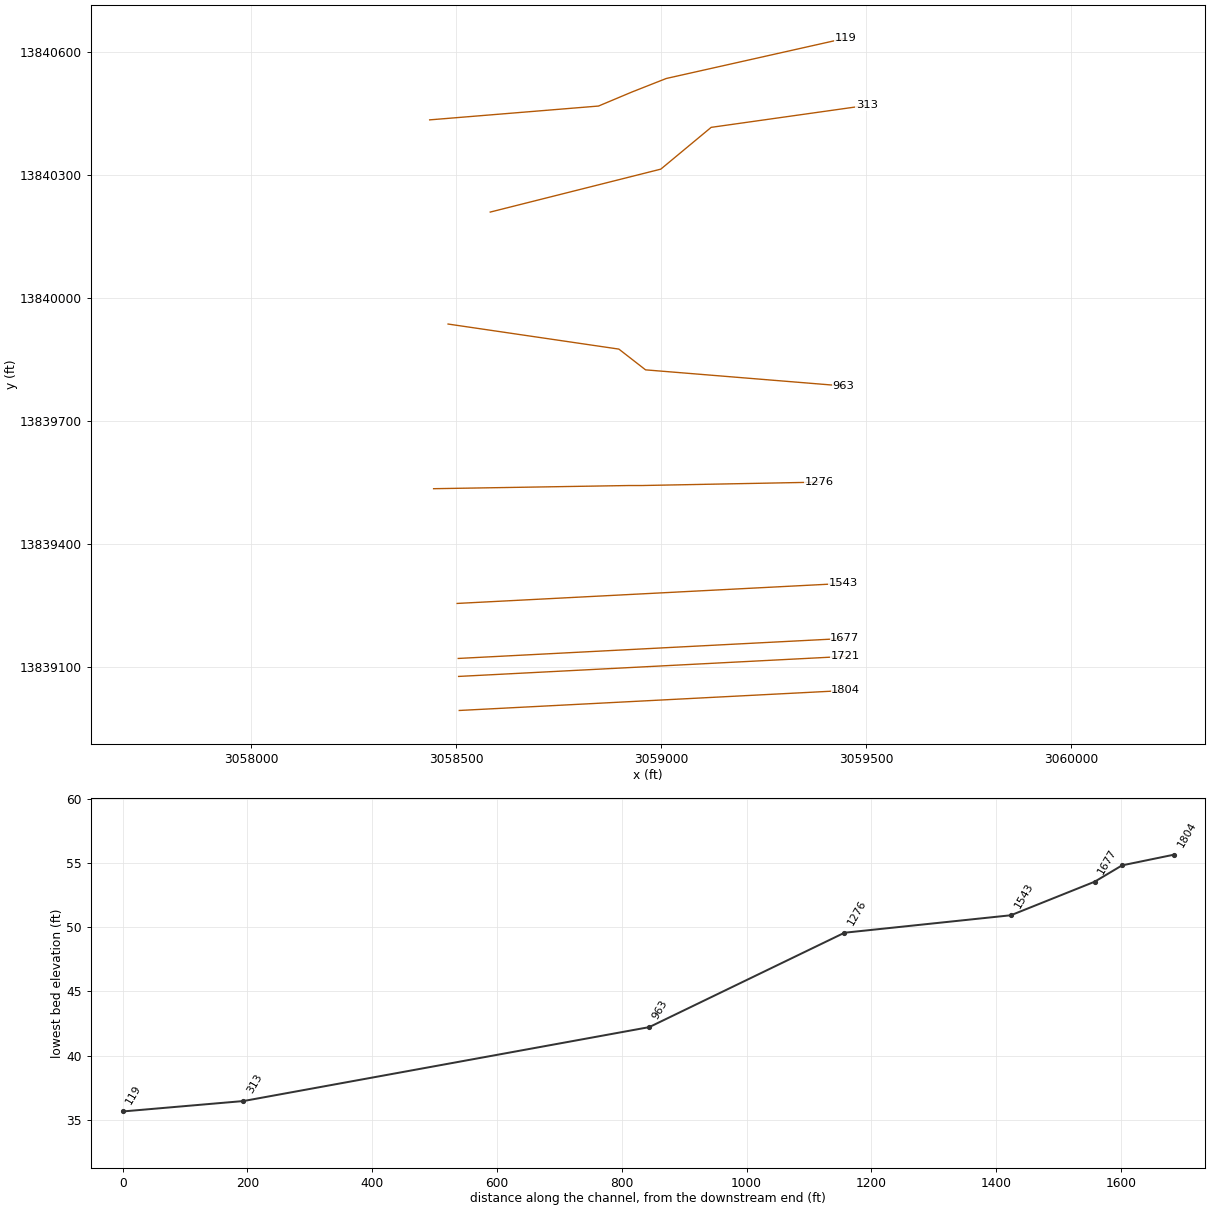
HEC-RAS study W157-00-00.prj: W157-00-00

--- W157-00-00.g01 (geometry) --- (continued)

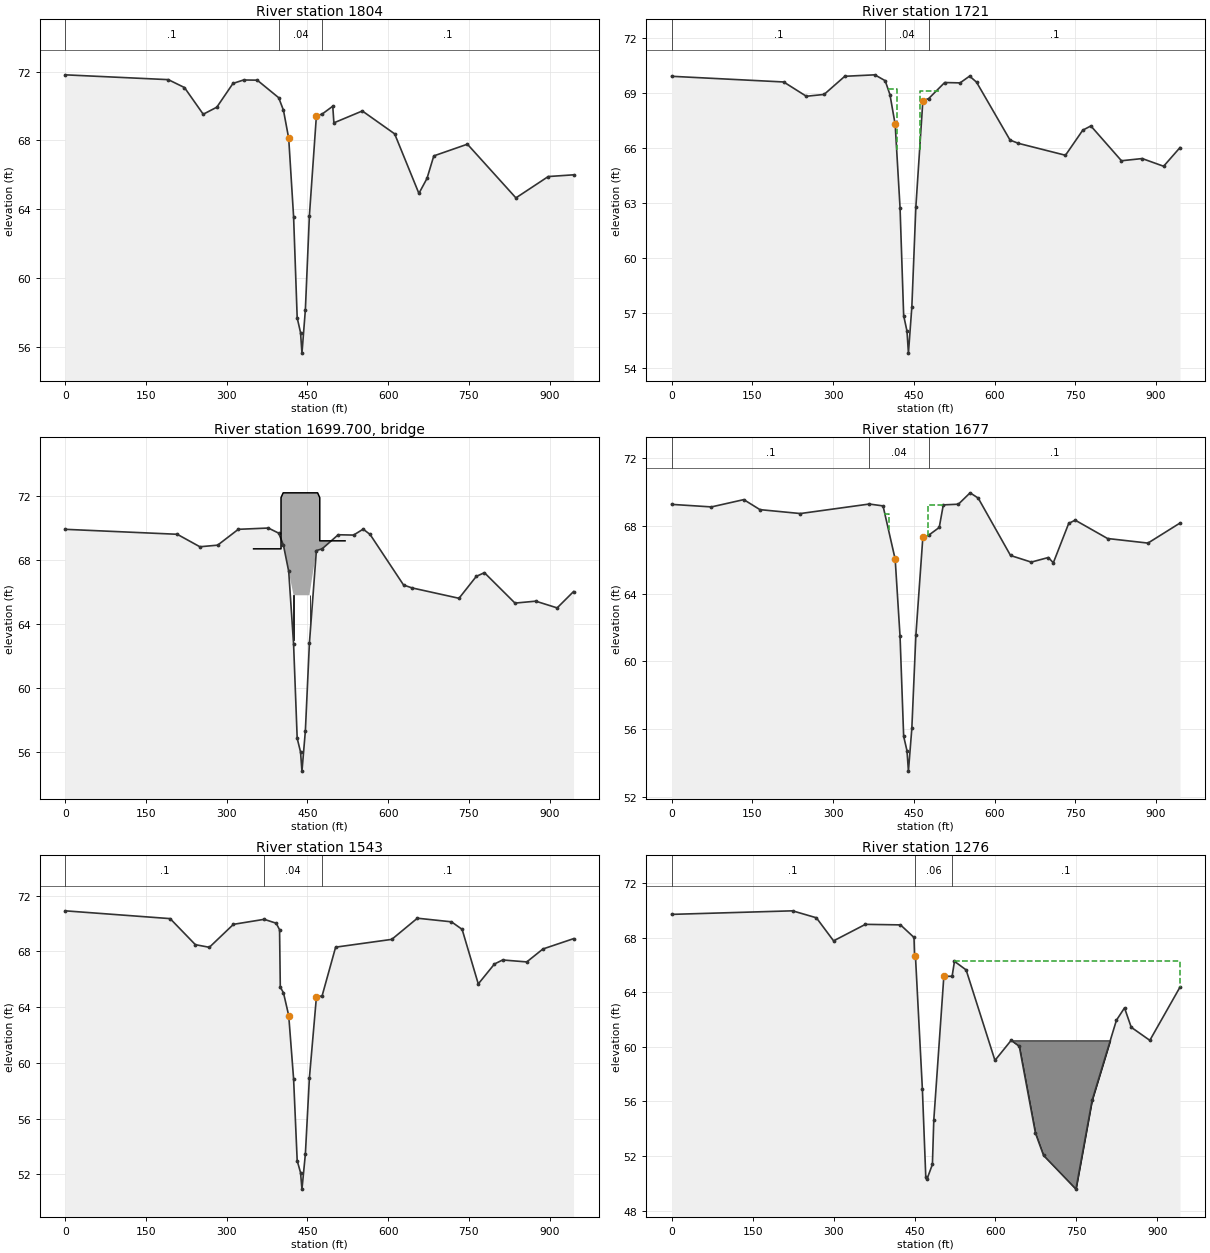
Type RM Length L Ch R = 1 ,1804    ,83.23,83.08,83.54
BEGIN DESCRIPTION:
Sta. 1804: edited bank stations
END DESCRIPTION:
XS GIS Cut Line= 3
      3058507.63     13838993.68     3058946.918    13839016.426
     3059450.877    13839042.521
#Sta/Elev= 30
       0   71.81  191.58   71.53  221.62   71.07  256.46   69.52   281.7   69.93
  311.74   71.31  331.46   71.51   356.8    71.5  396.69   70.48  405.57 69.7475
  415.29 68.1175  424.35 63.5751  431.05 57.6871  437.25 56.8378  439.91 55.6402
  446.25 58.1634  453.72 63.6259  466.72 69.4244  477.39 69.5296  497.14 69.9861
  499.23   69.02  552.06   69.71  612.14   68.38   657.2   64.92  672.22   65.79
  684.88    67.1  747.32   67.78  837.44   64.66  897.52    65.9  944.51      66
#Mann= 3 ,-1 , 0
       0      .1       0  396.69     .04       0  477.39      .1       0
Bank Sta=415.29,466.72
XS Rating Curve= 0
Exp/Cntr=.5,.3

Type RM Length L Ch R = 1 ,1721    ,43.9,43.89,43.93
Node Photo=F:\TSARP\Field-Survey\W157-00-00\PHOTOS\W157-00-S3\W157-00-S3p1.JPG
BEGIN DESCRIPTION:
Sta. 1721: surveyed section copied from River Station 1804
elevations of surveyed sections adjusted using channel slope
END DESCRIPTION:
XS GIS Cut Line= 3
     3058506.093    13839076.752      3058945.38    13839099.499
     3059449.339    13839125.594
#Sta/Elev= 30
       0   69.92  208.14   69.61  250.23   68.83  283.24   68.93  321.64   69.92
  377.45      70  396.69   69.68  405.57   68.92  415.29   67.29  424.35   62.74
  431.05   56.86  437.25   56.01  439.91   54.81  446.25   57.33  453.72   62.79
  466.72   68.59  477.39    68.7  507.29   69.58  535.85   69.56   553.6   69.93
  566.46    69.6   628.7   66.44  644.28   66.26   731.7   65.61  763.88   66.98
   778.9   67.21  835.74   65.31  874.26   65.43  914.08   65.01  944.51   66.03
#Mann= 3 ,-1 , 0
       0      .1       0  396.69     .04       0  477.39      .1       0
#XS Ineff= 2 ,-1
  401.81  418.08   69.24  460.66  496.44   69.13
Permanent Ineff=
       F       F
Bank Sta=415.29,466.72
XS Rating Curve= 0
Exp/Cntr=.5,.3

Type RM Length L Ch R = 3 ,1699.700,,,
BEGIN DESCRIPTION:
Bridge @ Riverview (Structure 3); pier on upstream section is for pipeline and does not exist on the downstream side.
END DESCRIPTION:
Bridge Culvert--1,0,-1,-1, 0
Deck Dist Width WeirC Skew NumUp NumDn MinLoCord MaxHiCord MaxSubmerge Is_Ogee
.5,43,2.6,0, 8, 8, , , .95, 0, 0,0,,
     350     401     401     405     469     473     473     520
    68.7    68.7    71.9    72.2    72.2    71.9    69.2    69.2
    65.8    65.8    65.8    65.8    65.8    65.8    65.8    65.8
     350     401     401     405     469     473     473     520
    68.7    68.7    71.9    72.2    72.2    71.9    69.2    69.2
    65.8    65.8    65.8    65.8    65.8    65.8    65.8    65.8
Pier Skew, UpSta & Num, DnSta & Num=  ,423.8, 2 ,423.8, 2 , 0 , 0 , 0 ,,
     1.1     1.1
       0      70
     1.1     1.1
       0      70
Pier Skew, UpSta & Num, DnSta & Num=  ,455.17, 2 ,455.17, 2 , 0 , 0 , 0 ,,
     1.1     1.1
       0      70
     1.1     1.1
       0      70
BR Coef=-1 , 1 , 1 ,.9, 0 ,,,.8,0,1.2,0,
WSPro=,,,, 1 ,,,, 0 ,,,, 0 ,,,,-1 ,-1 ,-1 , 0 , 0 , 0 , 0 , 0
BC Design=,, 0 ,, 0 ,,,,,,

Type RM Length L Ch R = 1 ,1677    ,134.31,134.28,134.3
Node Photo=F:\TSARP\Field-Survey\W157-00-00\PHOTOS\W157-00-S3\W157-00-S3p8.JPG
BEGIN DESCRIPTION:
Sta. 1677: surveyed section copied from River Station 1804
elevations of surveyed sections adjusted using channel slope
END DESCRIPTION:
XS GIS Cut Line= 3
     3058505.167     13839120.63     3058944.455    13839143.377
     3059448.414    13839169.472
#Sta/Elev= 30
       0   69.25   73.89    69.1  133.97   69.53  164.01   68.94  239.11   68.71
  367.17   69.27  392.73   69.16  415.29   66.02  424.35   61.47  431.05   55.59
  437.25   54.74  439.91   53.54  446.25   56.06  453.72   61.53  466.72   67.32
  477.39   67.43  497.14   67.89  504.73   69.22  532.72   69.26  554.53   69.93
  569.55   69.62  629.63   66.24  668.13   65.85  699.81   66.12  709.16   65.81
  737.73   68.13  749.79   68.32  809.87   67.24  884.97   66.97  944.51   68.15
#Mann= 3 ,-1 , 0
       0      .1       0  367.17     .04       0  477.39      .1       0
#XS Ineff= 2 ,-1
  395.21     403   68.68     476  505.19    69.2
Permanent Ineff=
       F       F
Bank Sta=415.29,466.72
XS Rating Curve= 0
Exp/Cntr=.5,.3

Type RM Length L Ch R = 1 ,1543    ,271.77,266.77,263.95
BEGIN DESCRIPTION:
Sta. 1543: surveyed section copied from River Station 1804
elevations of surveyed sections adjusted using channel slope
END DESCRIPTION:
XS GIS Cut Line= 3
     3058502.459    13839254.876     3058941.747    13839277.623
     3059445.706    13839303.718
#Sta/Elev= 30
       0   70.92  194.98   70.36  241.82   68.49  267.86    68.3   312.6   69.95
  369.73   70.31  392.02   70.03  398.29   69.56  399.66   65.44  405.57   65.03
  415.29    63.4  424.35   58.86  431.05   52.97  437.25   52.12  439.91   50.93
  446.25   53.45  453.72   58.91  466.72   64.71  477.39   64.82  502.46   68.31
  606.83   68.87  654.35   70.39  717.72   70.13  737.48   69.59  767.52   65.67
  797.56    67.1  812.76   67.39  857.64   67.25  887.68   68.18  944.51   68.92
#Mann= 3 ,-1 , 0
       0      .1       0  369.73     .04       0  477.39      .1       0
Bank Sta=415.29,466.72
XS Rating Curve= 0
Exp/Cntr=.3,.1

Type RM Length L Ch R = 1 ,1276    ,337.25,312.98,292.15
BEGIN DESCRIPTION:
Sta. 1276
END DESCRIPTION:
XS GIS Cut Line= 4
     3058445.005    13839534.882     3058919.908    13839542.594
     3058952.542    13839542.594      3059386.75    13839550.897
#Sta/Elev= 30
       0    69.7  223.98   69.96  268.15   69.45     300   67.76     359   68.97
  423.99   68.93  449.01   68.01   450.1 66.6467  451.73 66.6222  464.53 56.9118
  470.85  50.443  472.92 50.2846  483.12 51.3848  485.68 54.6182  504.32  65.164
  519.64 65.1657  524.01   66.26  545.61   65.63  599.03      59  629.03   60.47
  644.04   60.04  674.04   53.67  689.04   52.04  749.06   49.57  779.06   56.08
  824.07   61.94  839.07   62.85  851.51   61.43  885.98   60.47  941.89   64.37
#Mann= 3 ,-1 , 0
       0      .1       0   450.1     .06       0  519.64      .1       0
#XS Ineff= 2 , 0
       0                     524       0    66.3
Permanent Ineff=
       F       F
#Block Obstruct= 1 ,-1
  629.03     820   60.47
Bank Sta=451.73,504.32
XS Rating Curve= 0
Exp/Cntr=.3,.1

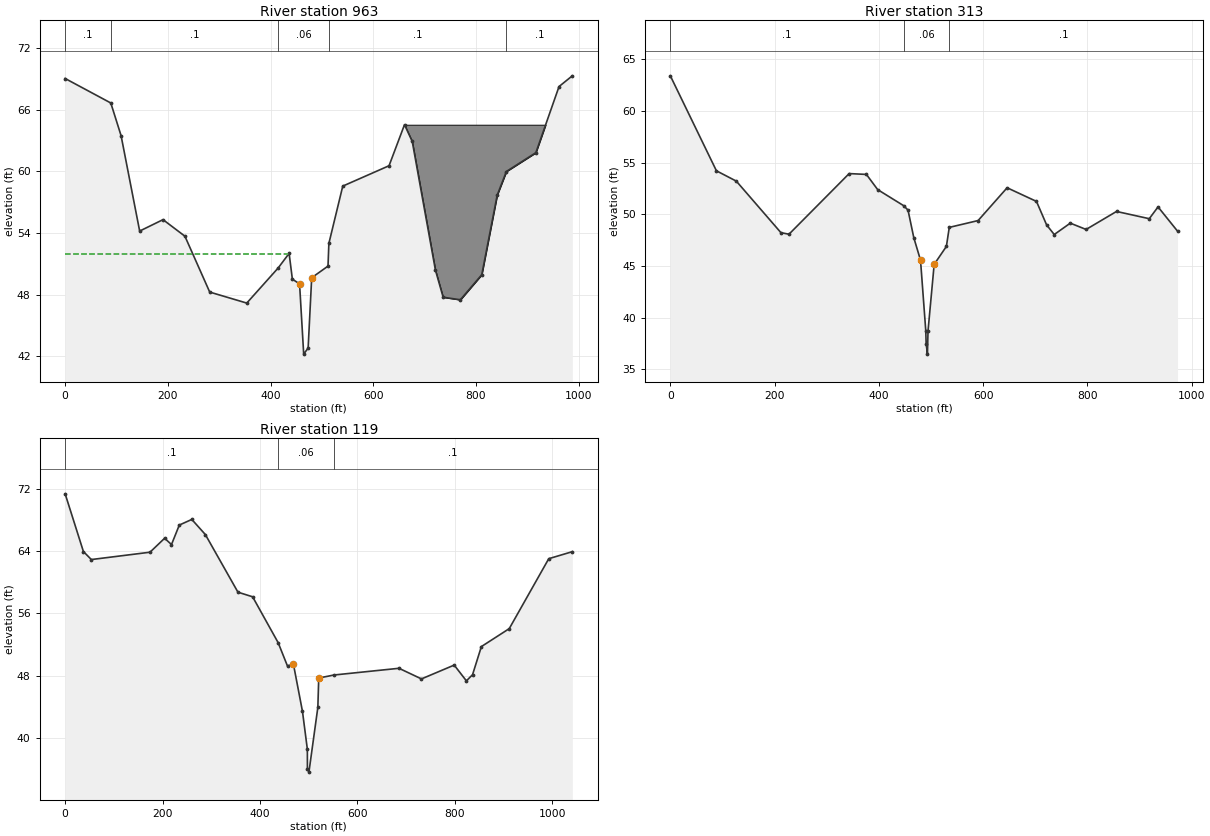
Type RM Length L Ch R = 1 ,963     ,609.28,650.46,706.34
BEGIN DESCRIPTION:
Sta. 963
END DESCRIPTION:
XS GIS Cut Line= 4
     3058480.364    13839936.691     3058897.124    13839875.541
     3058962.332     13839824.88     3059444.707    13839785.611
#Sta/Elev= 30
       0   69.02    88.9   66.64   108.9   63.47  145.13   54.19  190.61    55.3
  233.26   53.69  281.57   48.26  353.73   47.19  414.86    50.6   436.2   52.02
  442.55 49.5137  456.57 49.0565   464.6 42.2279  473.25 42.8225  480.17 49.6523
  511.96 50.7838  513.64   52.99   540.7   58.56  630.84   60.54  660.94   64.53
  675.99    62.9  721.14    50.4  736.19   47.76  769.72   47.51  811.43   49.95
  841.53   57.69  859.36   59.98  916.78   61.81  961.93   68.24  987.77   69.28
#Mann= 5 ,-1 , 0
       0      .1       0    88.9      .1       0  414.86     .06       0
  513.64      .1       0  859.36      .1       0
#XS Ineff= 2 , 0
       0   435.5      52  660.94       0   64.53
Permanent Ineff=
       F       F
#Block Obstruct= 1 ,-1
  660.94  987.77   64.53
Bank Sta=456.57,480.17
XS Rating Curve= 0
Exp/Cntr=.3,.1

Type RM Length L Ch R = 1 ,313     ,205.16,193.48,181.14
BEGIN DESCRIPTION:
Sta. 313
END DESCRIPTION:
XS GIS Cut Line= 4
     3058583.227    13840209.921     3058999.519    13840314.702
     3059122.419     13840416.66     3059502.567    13840470.294
#Sta/Elev= 30
       0   63.38    88.4    54.2   126.6    53.2  212.14   48.22  227.61   48.07
  343.02   53.93  376.13   53.85  397.76   52.38  447.52   50.83  455.95    50.4
  467.03 47.7321  479.93 45.5574  490.01 38.7285  490.68 37.5058  493.21 36.4791
  494.29 38.7061   506.1 45.1526  529.55 46.8913  535.08   48.73  590.38   49.39
  646.06   52.56  702.39   51.24   721.8   48.97  736.42   48.04  767.25   49.14
  797.54   48.53  855.89   50.27  918.73   49.57  935.55   50.71  972.88   48.37
#Mann= 3 ,-1 , 0
       0      .1       0  447.52     .06       0  535.08      .1       0
Bank Sta=479.93,506.1
XS Rating Curve= 0
Exp/Cntr=.3,.1

Type RM Length L Ch R = 1 ,119     ,,,
BEGIN DESCRIPTION:
Sta. 119: right bank station edited
END DESCRIPTION:
XS GIS Cut Line= 5
     3058435.362    13840434.935     3058847.498    13840468.666
     3058928.882    13840502.856     3059012.766    13840535.901
     3059451.136    13840634.232
#Sta/Elev= 30
       0   71.32   37.46   63.93   53.77    62.9  174.17   63.84  204.27   65.63
  218.31   64.82  234.37   67.32  260.04   68.04  287.87    66.1  354.77   58.72
  384.87   58.13  437.31   52.25   456.5 49.2514  468.45 49.5639  487.24 43.4455
  497.24  38.604  497.38 36.0959  500.47 35.6682   518.8 43.9722   520.6   47.72
  551.84   48.11   685.4   48.97  731.52   47.61  798.72   49.38  823.75   47.36
  836.39   48.15   854.5   51.75  911.73   54.05  992.85   63.01 1041.21   63.91
#Mann= 3 ,-1 , 0
       0      .1       0  437.31     .06       0  551.84      .1       0
Bank Sta=468.45,520.6
XS Rating Curve= 0
Exp/Cntr=.3,.1

Chan Stop Cuts=-1